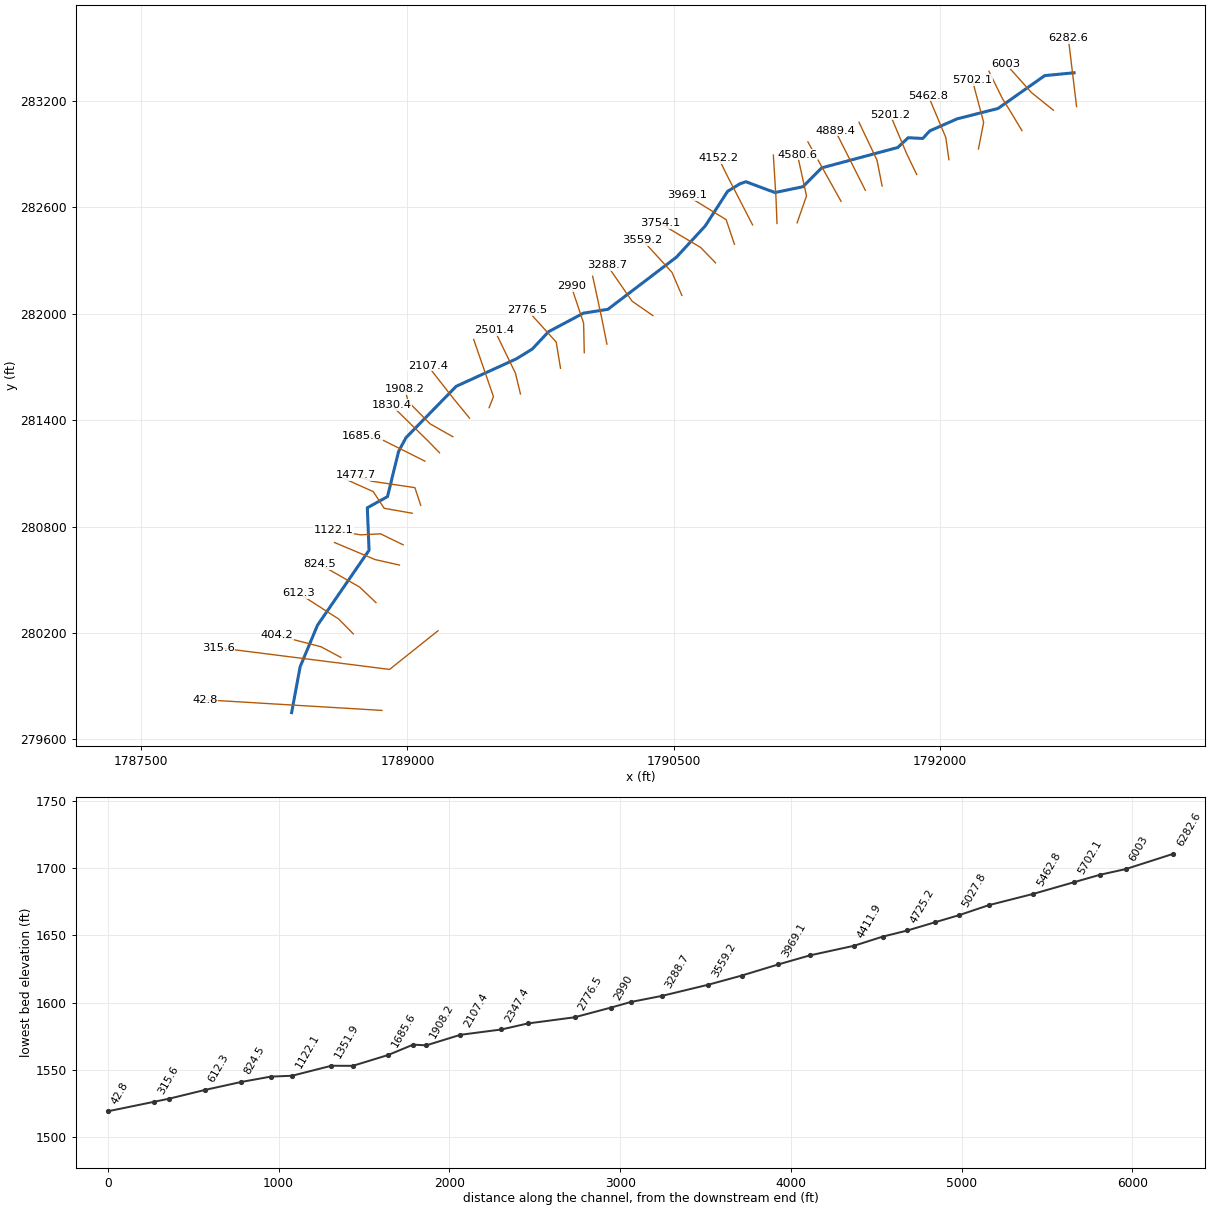
--- HuffCr.prj (project) ---

Proj Title=HuffCr
Current Plan=p01
Default Exp/Contr=0,0
English Units
Geom File=g01
Flow File=f01
Plan File=p01
BEGIN DESCRIPTION:
END DESCRIPTION:
DSS Export Rating Curves= 0
DSS Export Rating Curve Sorted= 0
DSS Export Volume Flow Curves= 0
DXF OffsetX= 0
DXF OffsetY= 0
DXF ScaleX= 0
DXF ScaleY= 0

--- HuffCr.p01 (plan) ---

Plan Title=Floodplain
Program Version=4.00
Geom File=g01
Flow File=f01
K Sum by GR=0
Std Step Tol=0.01
Critical Tol=0.01
Num of Std Step Trials=20
Max Error Tol=0.3
Flow Tol Ratio=0.001
Split Flow NTrial=30
Split Flow Tol=0.02
Split Flow Ratio=0.02
Log Output Level=0
Friction Slope Method=1
Unsteady Friction Slope Method=2
Unsteady Bridges Friction Slope Method=1
Global Log Level=0
CheckData=False
Run HTab=0
Run UNet=0
Run PostProcess=0
UNET Theta=0
UNET Theta Warmup=0
UNET ZTol=0
UNET ZSATol=0
UNET MxIter=0
UNET MaxInSteps=0
UNET DtIC=0
UNET DtMin=0
UNET MaxCRTS=0
UNET WFStab=0
UNET SFStab=0
UNET WFX=0
UNET SFX=0
UNET DSS MLevel=0
UNET DZMax Abort=0
UNET Convert EG Bridges=0
UNET Use Existing IB Tables=0
UNET Froude Limit=0
UNET Froude Power=0
Write IC File=0
Echo Input=False
Echo Output=False
Write Detailed=0

--- HuffCr.f01 (steady flow) ---

Flow Title=NFF Regression Equation
Program Version=4.00
Number of Profiles=1
Profile Names=P100yr
River Rch & RM=HuffCr,Main      ,6282.6
505.4044
River Rch & RM=HuffCr,Main      ,6003
743.0583
River Rch & RM=HuffCr,Main      ,5702.1
762.2925
River Rch & RM=HuffCr,Main      ,3288.7
826.3748
River Rch & RM=HuffCr,Main      ,2990
935.5017
River Rch & RM=HuffCr,Main      ,1477.7
969.7606
River Rch & RM=HuffCr,Main      ,1122.1
1133.280
River Rch & RM=HuffCr,Main      ,42.8
1143.382
Boundary for River Rch & Prof#=HuffCr,Main      ,1
Up Type=0
Dn Type=3
Dn Slope=0.027798

--- HuffCr.g01 (geometry) ---

Geom Title=USGS 10m DEM
Program Version=4.00

River Reach=HuffCr     ,Main
Reach XY= 30
     1792753.931      283358.749     1792589.003      283342.697
     1792325.644      283157.287     1792095.629      283098.923
     1791941.449      283030.859     1791902.230      282988.404
     1791819.958      282992.386     1791761.234      282937.259
     1791332.828      282822.508     1791227.415      282716.232
     1791070.160      282683.398     1790905.779      282744.395
     1790871.524      282732.194     1790803.012      282689.961
     1790677.573      282495.469     1790515.246      282319.167
     1790129.159      282025.024     1789991.667      282003.438
     1789795.049      281898.794     1789703.543      281801.188
     1789613.915      281745.816     1789275.112      281590.961
     1788991.795      281300.867     1788950.254      281222.892
     1788887.975      280968.727     1788774.415      280905.846
     1788784.269      280666.525     1788493.800      280243.725
     1788396.118      280009.639     1788348.179      279751.084

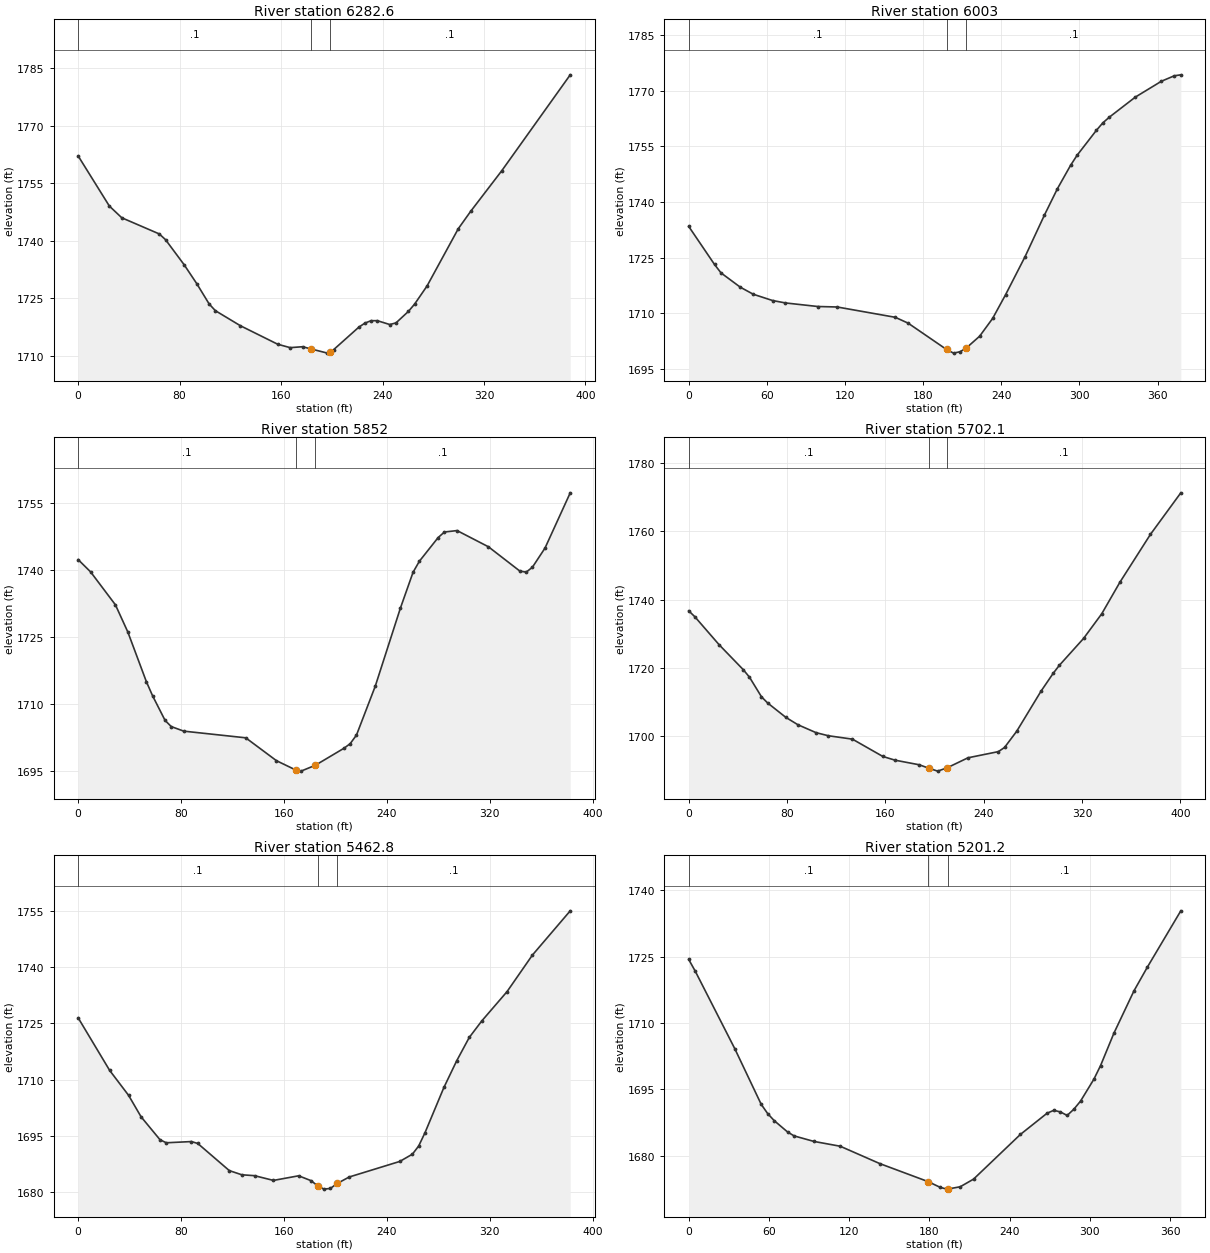
Type RM Length L Ch R = 1 ,6282.6,265.8,279.6,293.5
XS GIS Cut Line= 3
     1792768.279      283167.926     1792750.805      283314.457
     1792721.898      283553.126
#Sta/Elev= 30
       0 1762.11    24.6 1749.04    34.4 1745.98    64.0 1741.76    68.9 1740.27
    83.6 1733.72    93.5 1728.81   103.3 1723.50   108.2 1721.75   127.9 1717.83
   157.4 1712.99   167.2 1712.11   177.0 1712.35   183.6 1711.77   196.6 1710.68
   198.6 1711.05   201.5 1711.60   221.2 1717.42   226.1 1718.51   231.0 1719.14
   235.9 1719.14   245.7 1718.14   250.6 1718.56   260.4 1721.56   265.3 1723.47
   275.1 1728.19   299.7 1743.11   309.5 1747.66   334.0 1758.24   388.0 1783.26
#Mann= 3 , 0 , 0
       0     0.1       0   183.6   0.045       0   198.6     0.1       0
Bank Sta=   183.6,   198.6
Exp/Cntr=0.3,0.1

Type RM Length L Ch R = 1 ,6003,155,151,147
XS GIS Cut Line= 3
     1792637.665      283147.747     1792514.179      283247.227
     1792368.023      283410.782
#Sta/Elev= 30
       0 1733.44    19.8 1723.19    24.8 1720.91    39.6 1717.06    49.6 1715.15
    64.4 1713.46    74.3 1712.81    99.1 1711.85   114.0 1711.72   158.6 1708.94
   168.5 1707.36     198 1700.26   203.4 1699.28   208.4 1699.66     213 1700.61
   223.4 1703.84   233.4 1708.64   243.3 1715.01   258.3 1725.29   273.2 1736.52
   283.2 1743.65   293.2 1749.88   298.2 1752.60   313.1 1759.36   318.1 1761.39
   323.1 1762.92   343.0 1768.31   363.0 1772.58   372.9 1774.05   377.9 1774.31
#Mann= 3 , 0 , 0
       0     0.1       0     198   0.045       0     213     0.1       0
Bank Sta=     198,     213
Exp/Cntr=0.3,0.1

Type RM Length L Ch R = 1 ,5852,156.5,149.9,143.2
XS GIS Cut Line= 4
     1792460.449      283032.854     1792395.862      283140.511
     1792350.624      283213.588     1792274.836      283366.957
#Sta/Elev= 30
       0 1742.28     9.7 1739.53    29.0 1732.17    38.6 1726.13    53.1 1714.98
    57.9 1711.85    67.6 1706.36    72.4 1704.99    82.1 1703.97   130.3 1702.48
   154.2 1697.37   169.5 1695.25   173.3 1695.04   184.5 1696.36   206.7 1700.15
   211.5 1701.17   216.4 1703.09   231.0 1714.00   250.6 1731.48   260.4 1739.45
   265.3 1741.91   279.9 1747.20   284.8 1748.44   294.6 1748.76   319.0 1745.14
   343.5 1739.70   348.4 1739.48   353.2 1740.58   363.0 1744.86   382.6 1757.19
#Mann= 3 , 0 , 0
       0     0.1       0   169.5   0.045       0   184.5     0.1       0
Bank Sta=   169.5,   184.5
Exp/Cntr=0.3,0.1

Type RM Length L Ch R = 1 ,5702.1,236.3,239.3,242.4
XS GIS Cut Line= 3
     1792215.642      282928.893     1792245.067      283079.032
     1792181.269      283317.985
#Sta/Elev= 30
       0 1736.68     4.9 1734.97    24.7 1726.73    44.4 1719.38    49.4 1717.20
    59.2 1711.42    64.2 1709.61    79.0 1705.38    88.8 1703.22   103.6 1700.89
   113.5 1699.99   133.2 1698.98   157.9 1693.90   167.8 1692.81   187.6 1691.45
   195.1 1690.47   202.5 1689.59   210.1 1690.55   227.2 1693.51   251.9 1695.32
   256.9 1696.54   266.8 1701.30   286.6 1713.08   296.4 1718.28   301.4 1720.63
   321.2 1728.57   336.0 1735.82   350.8 1745.10   375.6 1759.14   400.3 1771.34
#Mann= 3 , 0 , 0
       0     0.1       0   195.1   0.045       0   210.1     0.1       0
Bank Sta=   195.1,   210.1
Exp/Cntr=0.3,0.1

Type RM Length L Ch R = 1 ,5462.8,261.6,261.6,260.5
XS GIS Cut Line= 3
     1792049.475      282868.365     1792031.634      282994.355
     1791933.037      283229.828
#Sta/Elev= 30
       0 1726.48    24.5 1712.48    39.2 1705.85    48.9 1700.14    63.6 1694.04
    68.5 1693.22    88.1 1693.54    93.0 1693.03   117.5 1685.81   127.2 1684.70
   137.1 1684.46   151.8 1683.20   171.4 1684.43   181.2 1683.11   186.4 1681.67
   191.1 1680.88   196.0 1681.06   201.4 1682.39   210.7 1684.11   250.0 1688.25
   259.8 1690.18   264.7 1692.36   269.6 1695.89   284.3 1707.94   294.2 1715.01
   304.0 1721.25   313.8 1725.67   333.4 1733.46   353.1 1743.18   382.5 1754.96
#Mann= 3 , 0 , 0
       0     0.1       0   186.4   0.045       0   201.4     0.1       0
Bank Sta=   186.4,   201.4
Exp/Cntr=0.3,0.1

Type RM Length L Ch R = 1 ,5201.2,172.5,173.4,175
XS GIS Cut Line= 3
     1791868.064      282785.094     1791810.472      282904.953
     1791719.279      283121.504
#Sta/Elev= 30
       0 1724.40     4.9 1721.74    34.5 1704.19    54.2 1691.64    59.1 1689.52
    64.0 1687.93    73.9 1685.39    78.8 1684.50    93.6 1683.25   113.3 1682.16
   143.0 1678.22   179.1 1674.15   188.0 1672.87   193.0 1672.46   194.1 1672.50
   203.0 1672.99   213.0 1674.72   248.0 1684.82   268.0 1689.63   273.0 1690.28
   278.0 1689.92   283.0 1689.12   288.0 1690.53   293.0 1692.36   303.0 1697.32
   308.0 1700.41   318.0 1707.75   333.0 1717.32   343.0 1722.67   368.0 1735.40
#Mann= 3 , 0 , 0
       0     0.1       0   179.1   0.045       0   194.1     0.1       0
Bank Sta=   179.1,   194.1
Exp/Cntr=0.3,0.1

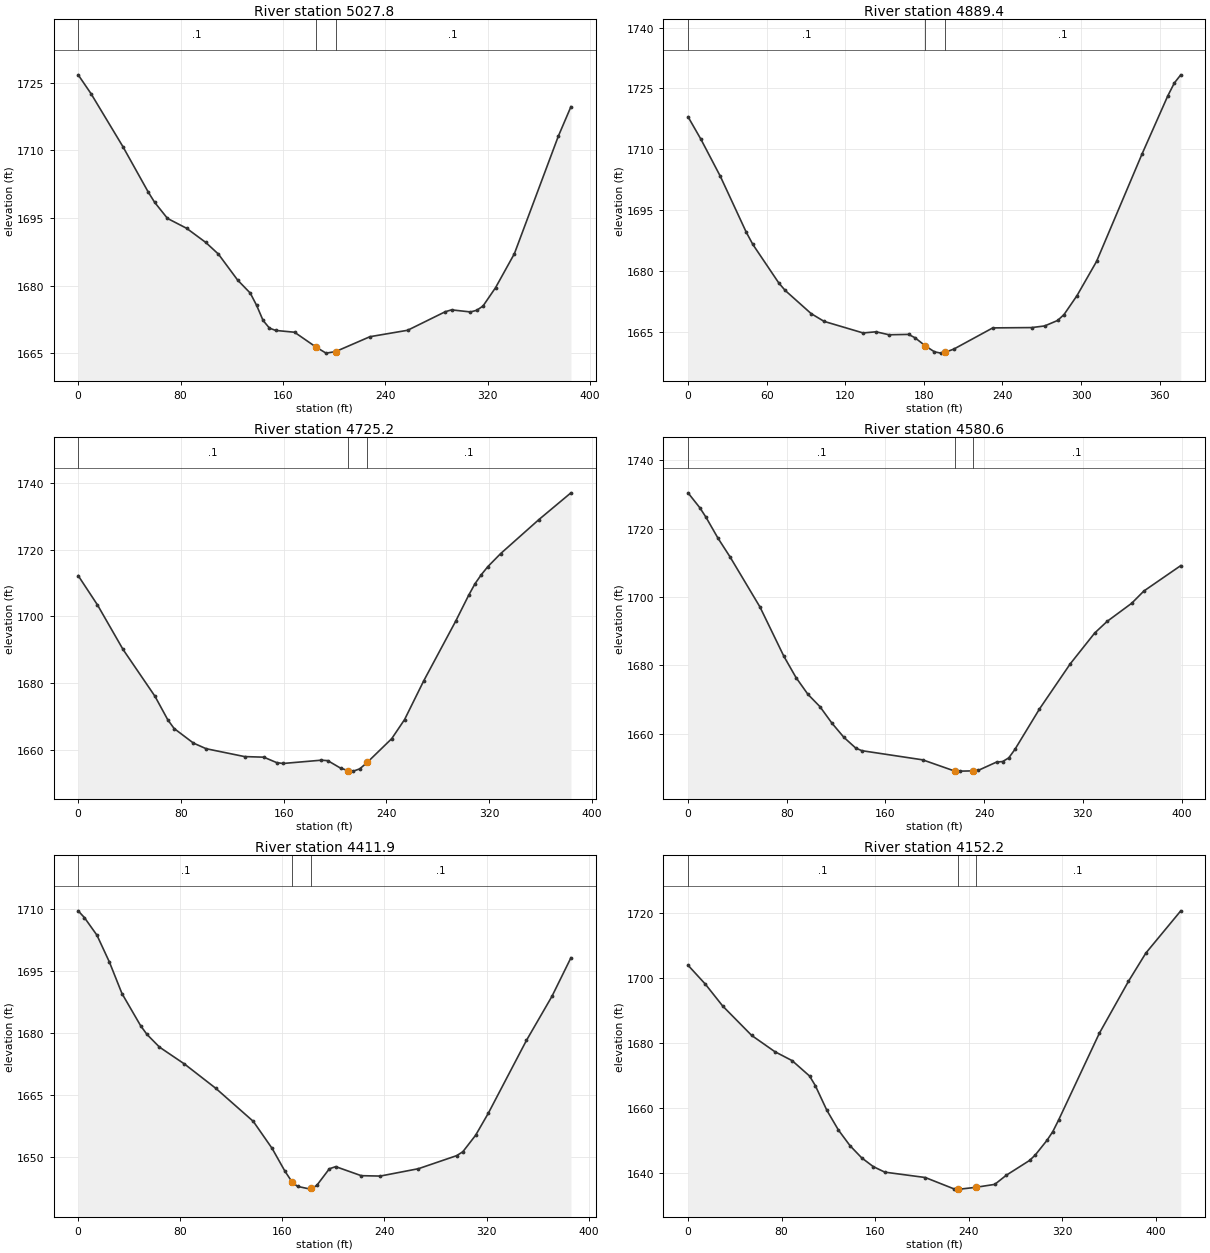
Type RM Length L Ch R = 1 ,5027.8,137.3,138.5,139.6
XS GIS Cut Line= 3
     1791673.370      282720.137     1791644.206      282866.759
     1791543.161      283079.613
#Sta/Elev= 30
       0 1726.74    10.0 1722.58    34.9 1710.85    54.8 1700.73    59.8 1698.46
    69.8 1694.91    84.7 1692.73    99.7 1689.59   109.6 1687.00   124.6 1681.25
   134.5 1678.35   139.5 1675.61   144.5 1672.29   149.5 1670.59   154.4 1670.08
   169.1 1669.68   186.1 1666.35   193.7 1665.05   201.1 1665.38   228.0 1668.69
   257.5 1670.12   286.9 1674.23   291.8 1674.64   306.6 1674.18   311.5 1674.55
   316.4 1675.50   326.2 1679.57   340.9 1687.09   375.3 1713.18   385.1 1719.68
#Mann= 3 , 0 , 0
       0     0.1       0   186.1   0.045       0   201.1     0.1       0
Bank Sta=   186.1,   201.1
Exp/Cntr=0.3,0.1

Type RM Length L Ch R = 1 ,4889.4,163.9,164.2,164.5
XS GIS Cut Line= 2
     1791578.852      282696.142     1791409.505      283031.980
#Sta/Elev= 30
       0 1718.04     9.9 1712.47    24.7 1703.36    44.5 1689.59    49.5 1686.60
    69.3 1677.12    74.2 1675.28    94.0 1669.58   103.9 1667.67   133.6 1664.83
   143.5 1665.11   153.4 1664.38   168.3 1664.47   173.2 1663.66   181.2 1661.63
   188.1 1660.18   193.0 1659.86   196.2 1660.05   202.9 1660.86   232.6 1666.07
   262.3 1666.15   272.2 1666.55   282.1 1667.90   287.0 1669.36   296.9 1674.02
   311.8 1682.42   346.4 1708.78   366.2 1723.19   371.2 1726.36   376.1 1728.36
#Mann= 3 , 0 , 0
       0     0.1       0   181.2   0.045       0   196.2     0.1       0
Bank Sta=   181.2,   196.2
Exp/Cntr=0.3,0.1

Type RM Length L Ch R = 1 ,4725.2,154.8,144.6,137.5
XS GIS Cut Line= 2
     1791442.119      282633.766     1791255.406      282968.908
#Sta/Elev= 30
       0 1712.23    15.0 1703.46    34.9 1690.12    59.8 1676.06    69.8 1668.99
    74.7 1666.41    89.7 1662.05    99.6 1660.36   129.5 1658.00   144.5 1657.82
   154.4 1656.21   159.4 1655.93   189.3 1656.92   194.3 1656.78   204.3 1654.53
   210.1 1653.81   214.2 1653.64   219.2 1654.32   225.1 1656.28   244.1 1663.38
   254.1 1669.10   269.0 1680.70   294.0 1698.67   303.9 1706.28   308.9 1709.79
   313.9 1712.55   318.9 1714.92   328.8 1718.80   358.7 1729.04   383.6 1737.04
#Mann= 3 , 0 , 0
       0     0.1       0   210.1   0.045       0   225.1     0.1       0
Bank Sta=   210.1,   225.1
Exp/Cntr=0.3,0.1

Type RM Length L Ch R = 1 ,4580.6,169.1,168.7,165.1
XS GIS Cut Line= 3
     1791194.655      282512.696     1791247.531      282664.072
     1791196.347      282897.496
#Sta/Elev= 30
       0 1730.51     9.7 1726.09    14.6 1723.34    24.3 1717.23    34.0 1711.80
    58.3 1697.11    77.7 1682.67    87.5 1676.47    97.2 1671.54   106.9 1667.95
   116.6 1663.13   126.3 1658.97   136.0 1655.80   140.9 1655.06   190.2 1652.38
     216 1649.11   220.1 1649.08     231 1649.15   235.0 1649.27   250.0 1651.73
   254.9 1651.88   259.9 1652.95   264.9 1655.44   284.8 1667.27   309.7 1680.46
   329.6 1689.51   339.6 1692.89   359.5 1698.19   369.4 1701.78   399.3 1709.22
#Mann= 3 , 0 , 0
       0     0.1       0     216   0.045       0     231     0.1       0
Bank Sta=     216,     231
Exp/Cntr=0.3,0.1

Type RM Length L Ch R = 1 ,4411.9,249.9,259.7,269.5
XS GIS Cut Line= 3
     1791081.469      282509.061     1791075.823      282651.006
     1791060.744      282894.598
#Sta/Elev= 30
       0 1709.57     4.9 1707.93    14.7 1703.68    24.5 1697.16    34.3 1689.57
    49.0 1681.75    53.9 1679.68    63.7 1676.61    83.3 1672.52   107.8 1666.65
   137.2 1658.65   152.0 1652.09   162.0 1646.60   167.8 1643.90   171.9 1642.92
   181.9 1642.26   182.8 1642.42   186.9 1643.14   196.8 1647.18   201.8 1647.70
   221.8 1645.51   236.7 1645.42   266.6 1647.20   296.5 1650.35   301.4 1651.30
   311.4 1655.29   321.4 1660.64   351.2 1678.21   371.2 1688.88   386.1 1698.22
#Mann= 3 , 0 , 0
       0     0.1       0   167.8   0.045       0   182.8     0.1       0
Bank Sta=   167.8,   182.8
Exp/Cntr=0.3,0.1

Type RM Length L Ch R = 1 ,4152.2,171.1,183,195
XS GIS Cut Line= 3
     1790943.945      282500.868     1790807.871      282764.682
     1790752.902      282876.279
#Sta/Elev= 30
       0 1703.88    14.8 1698.07    29.7 1691.32    54.4 1682.31    74.2 1677.32
    89.0 1674.56   103.9 1669.83   108.8 1666.90   118.7 1659.29   128.6 1653.22
   138.5 1648.42   148.4 1644.71   158.3 1642.01   168.2 1640.30   202.8 1638.65
   227.6 1635.12   230.9 1635.09   232.5 1635.08   245.9 1635.63   262.2 1636.54
   272.1 1639.36   291.9 1643.88   296.8 1645.56   306.8 1650.06   311.8 1652.75
   316.7 1656.26   351.6 1682.98   376.5 1698.94   391.4 1707.64   421.2 1720.59
#Mann= 3 , 0 , 0
       0     0.1       0   230.9   0.045       0   245.9     0.1       0
Bank Sta=   230.9,   245.9
Exp/Cntr=0.3,0.1

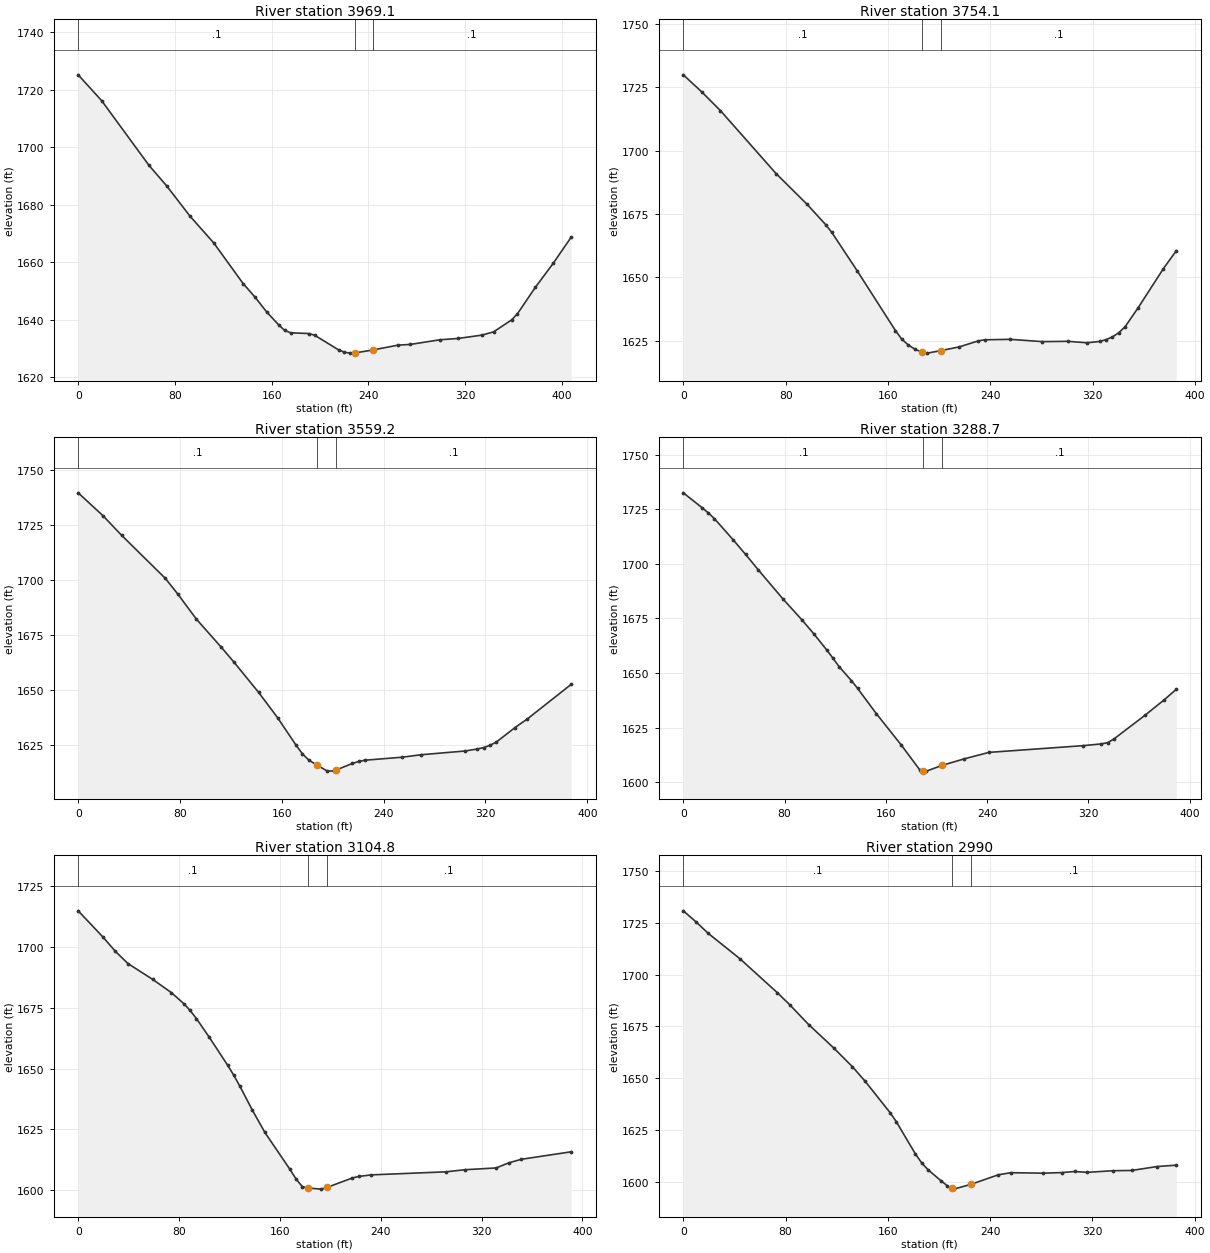
Type RM Length L Ch R = 1 ,3969.1,214.7,215.1,215.3
XS GIS Cut Line= 3
     1790841.615      282391.785     1790795.112      282530.369
     1790572.302      282667.381
#Sta/Elev= 30
       0 1725.20    19.5 1716.17    58.5 1693.74    73.1 1686.62    92.6 1675.99
   112.1 1666.75   136.4 1652.61   146.2 1647.92   156.0 1642.68   165.9 1638.21
   170.8 1636.30   175.8 1635.47   190.6 1635.23   195.5 1634.66   215.3 1629.56
   220.2 1628.73   225.1 1628.41   228.7 1628.47   243.7 1629.50   264.6 1631.20
   274.5 1631.42   299.2 1633.06   314.0 1633.50   333.7 1634.66   343.6 1635.81
   358.4 1639.94   363.3 1642.10   378.1 1651.29   392.9 1659.66   407.7 1668.72
#Mann= 3 , 0 , 0
       0     0.1       0   228.7   0.045       0   243.7     0.1       0
Bank Sta=   228.7,   243.7
Exp/Cntr=0.3,0.1

Type RM Length L Ch R = 1 ,3754.1,201.6,194.9,188.3
XS GIS Cut Line= 3
     1790735.466      282287.088     1790651.276      282373.774
     1790424.102      282509.213
#Sta/Elev= 30
       0 1729.97    14.5 1723.18    29.0 1715.84    72.5 1690.98    96.7 1678.87
   111.2 1670.86   116.0 1667.79   135.8 1652.67   165.8 1629.00   170.7 1625.64
   175.7 1623.37   180.7 1621.75   186.4 1620.48   190.7 1620.10   201.4 1621.10
   215.7 1622.57   230.6 1624.94   235.6 1625.37   255.6 1625.54   280.5 1624.64
   300.5 1624.76   315.5 1624.19   325.4 1624.71   330.4 1625.44   335.4 1626.50
   340.4 1628.15   345.4 1630.59   355.4 1637.94   375.3 1653.51   385.3 1660.51
#Mann= 3 , 0 , 0
       0     0.1       0   186.4   0.045       0   201.4     0.1       0
Bank Sta=   186.4,   201.4
Exp/Cntr=0.3,0.1

Type RM Length L Ch R = 1 ,3559.2,273.5,270.5,267.4
XS GIS Cut Line= 3
     1790545.774      282102.983     1790490.041      282233.418
     1790324.537      282414.641
#Sta/Elev= 30
       0 1739.65    19.6 1729.20    34.2 1720.33    68.5 1700.81    78.3 1693.67
    92.9 1682.30   112.5 1669.52   122.3 1662.87   141.8 1649.05   156.6 1637.64
   171.3 1625.01   176.2 1621.19   181.1 1618.39   187.3 1616.16   195.8 1613.33
   200.8 1613.43   202.3 1613.77   215.5 1616.81   220.4 1617.71   225.3 1618.28
   254.7 1619.66   269.5 1620.77   303.8 1622.46   313.6 1623.37   318.6 1624.03
   323.5 1625.04   328.4 1626.47   343.1 1633.05   352.9 1637.01   387.3 1652.69
#Mann= 3 , 0 , 0
       0     0.1       0   187.3   0.045       0   202.3     0.1       0
Bank Sta=   187.3,   202.3
Exp/Cntr=0.3,0.1

Type RM Length L Ch R = 1 ,3288.7,193,183.9,174.8
XS GIS Cut Line= 3
     1790382.195      281989.670     1790265.008      282071.023
     1790124.652      282274.017
#Sta/Elev= 30
       0 1732.49    14.8 1725.68    19.7 1723.31    24.6 1720.64    39.4 1710.96
    49.2 1704.28    59.0 1697.35    78.7 1683.90    93.5 1674.43   103.3 1667.77
   113.1 1660.65   118.1 1656.86   123.0 1652.95   132.8 1646.48   137.7 1642.90
   152.5 1631.34   172.3 1616.90   187.1 1605.38   189.7 1605.21   192.0 1605.05
   204.7 1607.74   221.6 1610.62   241.4 1613.63   315.4 1616.70   330.2 1617.51
   335.2 1618.06   340.1 1619.76   364.8 1630.68   379.6 1637.58   389.4 1642.51
#Mann= 3 , 0 , 0
       0     0.1       0   189.7   0.045       0   204.7     0.1       0
Bank Sta=   189.7,   204.7
Exp/Cntr=0.3,0.1

Type RM Length L Ch R = 1 ,3104.8,111.9,114.8,117.7
XS GIS Cut Line= 3
     1790123.660      281828.567     1790095.653      281968.947
     1790043.455      282211.379
#Sta/Elev= 30
       0 1714.96    19.7 1704.16    29.6 1698.23    39.5 1693.26    59.2 1686.72
    74.0 1681.29    83.9 1676.72    88.8 1673.96    93.8 1670.64   103.7 1663.18
   118.5 1651.52   123.4 1647.36   128.3 1642.78   138.2 1632.94   148.1 1623.80
   168.0 1608.60   172.9 1604.58   177.9 1601.45   182.3 1600.93   192.7 1600.46
   197.3 1601.14   217.5 1605.05   222.5 1605.66   232.4 1606.32   291.9 1607.58
   306.8 1608.44   331.6 1609.18   341.5 1611.25   351.5 1612.73   391.1 1615.82
#Mann= 3 , 0 , 0
       0     0.1       0   182.3   0.045       0   197.3     0.1       0
Bank Sta=   182.3,   197.3
Exp/Cntr=0.3,0.1

Type RM Length L Ch R = 1 ,2990,204.2,213.5,222.8
XS GIS Cut Line= 3
     1789996.097      281780.305     1789992.417      281946.907
     1789922.819      282154.541
#Sta/Elev= 30
       0 1730.82     9.8 1725.56    19.6 1719.87    44.1 1707.76    73.5 1691.29
    83.3 1685.40    98.0 1675.89   117.6 1664.58   132.3 1655.48   142.1 1648.56
   161.7 1633.34   166.6 1628.94   181.6 1613.28   186.6 1608.90   191.5 1605.66
   201.5 1600.43   206.5 1597.96   209.8 1596.88   211.4 1596.35   224.8 1598.62
   246.3 1603.26   256.2 1604.29   281.1 1604.07   296.0 1604.34   306.0 1604.87
   316.0 1604.46   335.9 1605.24   350.8 1605.38   370.7 1607.27   385.6 1607.93
#Mann= 3 , 0 , 0
       0     0.1       0   209.8   0.045       0   224.8     0.1       0
Bank Sta=   209.8,   224.8
Exp/Cntr=0.3,0.1

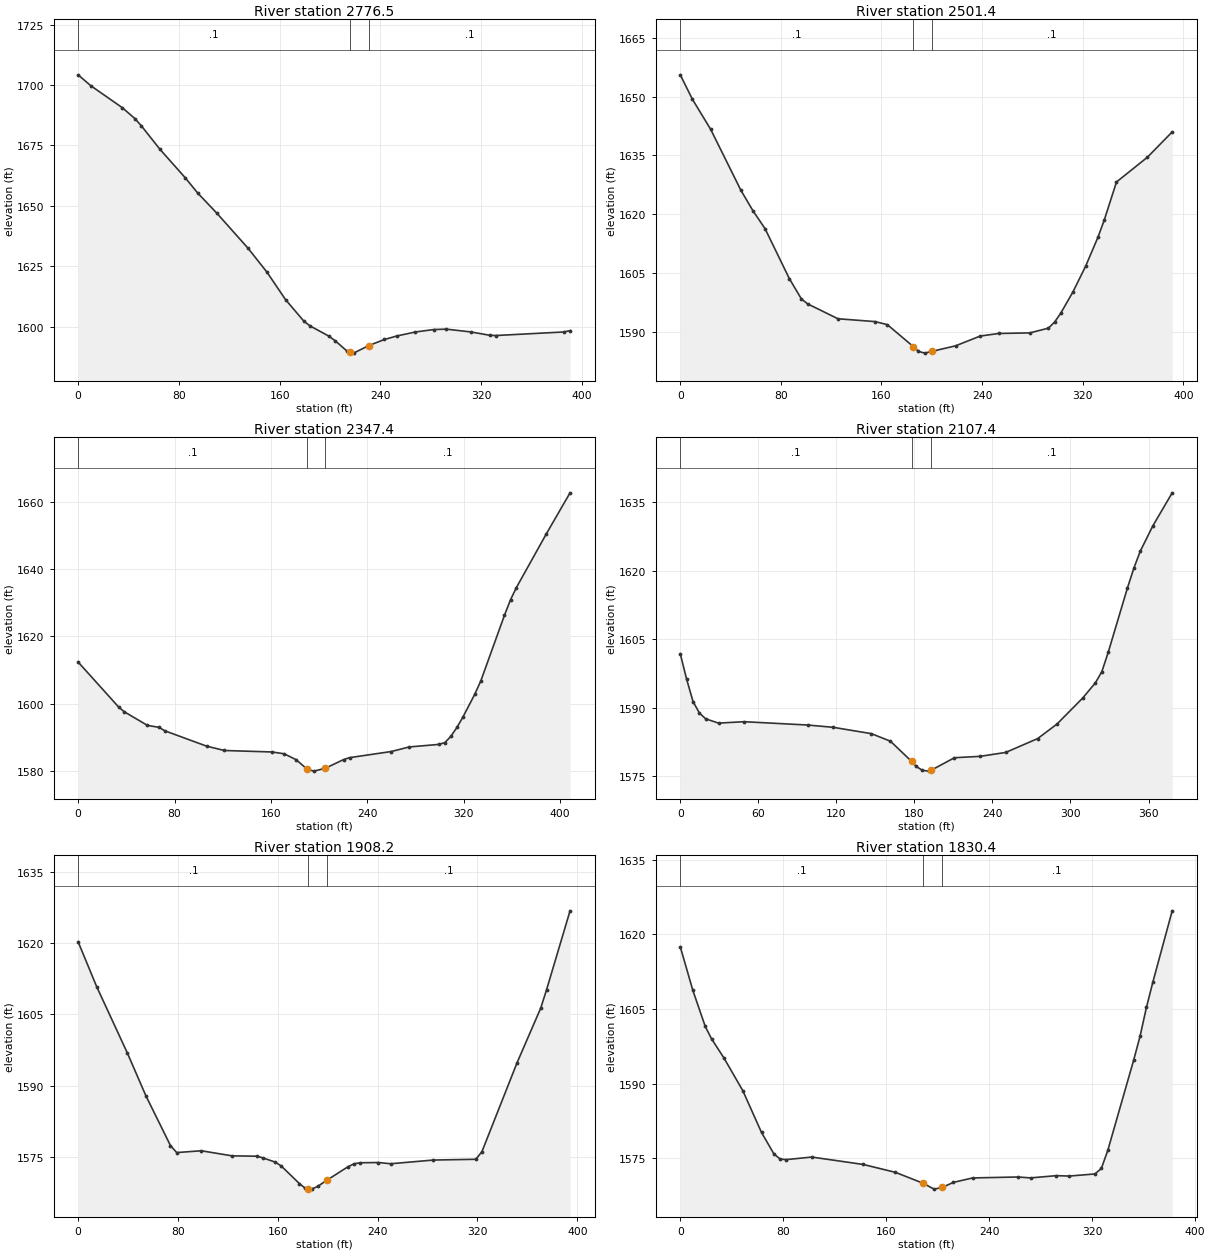
Type RM Length L Ch R = 1 ,2776.5,281.4,275.1,268.8
XS GIS Cut Line= 3
     1789862.341      281692.222     1789838.141      281840.191
     1789676.906      282018.825
#Sta/Elev= 30
       0 1704.20    10.0 1699.72    35.0 1690.64    45.0 1686.14    50.0 1683.24
    65.0 1673.39    85.0 1661.66    95.0 1655.29   110.0 1647.07   134.9 1632.51
   149.9 1622.63   164.7 1611.24   179.4 1602.24   184.3 1600.33   199.0 1596.18
   204.0 1594.28   213.8 1589.83   215.8 1589.54   218.7 1589.12   230.8 1592.24
   243.2 1594.76   253.1 1596.21   267.8 1597.87   282.5 1598.87   292.4 1599.04
   312.0 1597.87   326.7 1596.51   331.6 1596.40   385.7 1597.87   390.6 1598.42
#Mann= 3 , 0 , 0
       0     0.1       0   215.8   0.045       0   230.8     0.1       0
Bank Sta=   215.8,   230.8
Exp/Cntr=0.3,0.1

Type RM Length L Ch R = 1 ,2501.4,156.8,154.1,151.3
XS GIS Cut Line= 3
     1789636.718      281547.971     1789608.468      281665.036
     1789490.152      281908.628
#Sta/Elev= 30
       0 1655.61     9.6 1649.38    24.1 1641.72    48.2 1626.11    57.8 1620.87
    67.4 1616.31    86.7 1603.56    96.3 1598.35   101.2 1597.10   125.4 1593.28
   154.9 1592.56   164.7 1591.77   185.3 1586.18   189.4 1584.96   194.3 1584.50
   200.3 1584.97   218.9 1586.36   238.6 1588.87   253.4 1589.52   278.0 1589.67
   292.8 1590.89   297.7 1592.44   302.6 1594.72   312.4 1600.22   322.3 1606.67
   332.2 1614.14   337.1 1618.43   346.9 1628.23   371.5 1634.56   391.2 1641.02
#Mann= 3 , 0 , 0
       0     0.1       0   185.3   0.045       0   200.3     0.1       0
Bank Sta=   185.3,   200.3
Exp/Cntr=0.3,0.1

Type RM Length L Ch R = 1 ,2347.4,232.6,239.9,247.3
XS GIS Cut Line= 3
     1789460.270      281470.352     1789484.686      281532.814
     1789373.330      281855.284
#Sta/Elev= 30
       0 1612.40    33.5 1599.10    38.3 1597.65    57.5 1593.61    67.1 1593.03
    72.0 1591.99   106.6 1587.45   121.4 1586.16   161.0 1585.72   170.9 1585.19
   180.8 1583.46     190 1580.63   195.6 1580.04     205 1580.87   220.3 1583.47
   225.3 1584.04   259.9 1585.86   274.7 1587.21   299.4 1587.97   304.4 1588.53
   309.3 1590.36   314.3 1592.99   319.2 1596.01   329.1 1602.82   334.1 1606.76
   353.8 1626.29   358.8 1630.87   363.7 1634.51   388.4 1650.35   408.2 1662.60
#Mann= 3 , 0 , 0
       0     0.1       0     190   0.045       0     205     0.1       0
Bank Sta=     190,     205
Exp/Cntr=0.3,0.1

Type RM Length L Ch R = 1 ,2107.4,196.6,199.2,201.8
XS GIS Cut Line= 3
     1789349.815      281411.638     1789253.680      281529.054
     1789114.484      281707.688
#Sta/Elev= 30
       0 1601.80     4.9 1596.21     9.8 1591.34    14.7 1588.82    19.6 1587.54
    29.4 1586.61    49.0 1586.92    97.9 1586.19   117.5 1585.69   146.9 1584.30
   161.6 1582.64   177.9 1578.20   181.3 1577.12   186.2 1576.24   191.1 1576.08
   192.9 1576.28   210.8 1579.02   230.5 1579.32   250.2 1580.18   274.8 1583.22
   289.6 1586.40   309.3 1592.08   319.1 1595.42   324.1 1597.88   329.0 1602.12
   343.8 1616.26   348.7 1620.55   353.6 1624.28   363.4 1629.91   378.2 1637.11
#Mann= 3 , 0 , 0
       0     0.1       0   177.9   0.045       0   192.9     0.1       0
Bank Sta=   177.9,   192.9
Exp/Cntr=0.3,0.1

Type RM Length L Ch R = 1 ,1908.2,77.4,77.8,78.3
XS GIS Cut Line= 4
     1789255.839      281306.607     1789127.083      281379.685
     1789004.127      281504.961     1788986.728      281573.399
#Sta/Elev= 30
       0 1620.23    14.8 1610.84    39.5 1596.84    54.3 1587.88    74.0 1577.42
    79.0 1575.95    98.7 1576.33   123.4 1575.26   143.1 1575.19   148.0 1574.84
   157.8 1573.96   162.7 1573.15   177.3 1569.44   182.2 1568.41   184.6 1568.34
   187.1 1568.27   191.9 1568.83   199.6 1570.19   216.3 1572.98   221.2 1573.60
   226.1 1573.81   240.7 1573.86   250.4 1573.60   284.6 1574.38   318.7 1574.54
   323.6 1576.15   351.8 1594.86   370.7 1606.29   375.4 1610.17   394.2 1626.74
#Mann= 3 , 0 , 0
       0     0.1       0   184.6   0.045       0   199.6     0.1       0
Bank Sta=   184.6,   199.6
Exp/Cntr=0.3,0.1

Type RM Length L Ch R = 1 ,1830.4,137.6,144.8,152.1
XS GIS Cut Line= 3
     1789180.997      281216.157     1789116.644      281282.248
     1788909.464      281485.130
#Sta/Elev= 30
       0 1617.49     9.7 1608.78    19.4 1601.48    24.3 1598.98    34.0 1595.10
    48.6 1588.55    63.1 1580.16    72.8 1575.82    77.7 1574.79    82.5 1574.70
   102.2 1575.21   142.2 1573.72   167.2 1572.13   188.4 1569.97   197.2 1568.76
   203.4 1569.09   212.2 1570.12   227.2 1571.01   262.2 1571.20   272.2 1571.02
   292.2 1571.47   302.2 1571.39   322.2 1571.81   327.2 1572.94   332.2 1576.59
   352.2 1594.64   357.2 1599.47   362.2 1605.32   367.2 1610.42   382.2 1624.73
#Mann= 3 , 0 , 0
       0     0.1       0   188.4   0.045       0   203.4     0.1       0
Bank Sta=   188.4,   203.4
Exp/Cntr=0.3,0.1

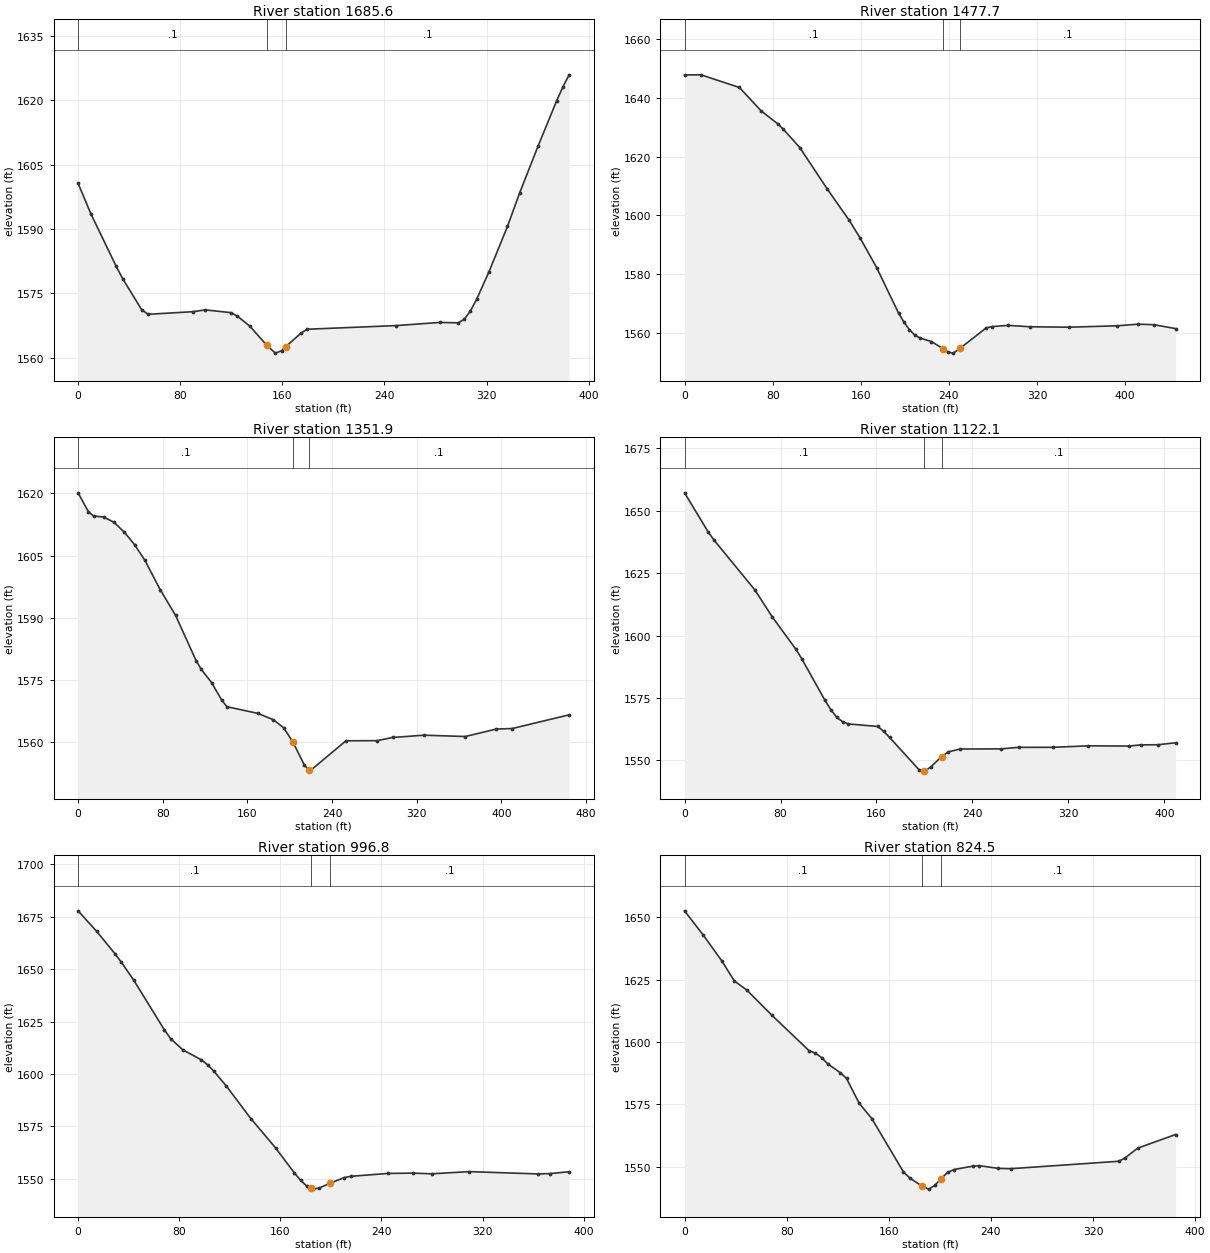
Type RM Length L Ch R = 1 ,1685.6,200.7,207.9,215
XS GIS Cut Line= 3
     1789098.600      281168.959     1788866.852      281284.948
     1788744.415      281312.591
#Sta/Elev= 30
       0 1600.67    10.0 1593.56    29.9 1581.30    34.9 1578.47    49.8 1571.24
    54.8 1570.16    89.7 1570.76    99.7 1571.18   119.6 1570.55   124.6 1569.78
   134.6 1567.38   147.7 1563.00   154.5 1561.12   159.5 1561.68   162.7 1562.62
   174.4 1565.72   179.4 1566.68   249.2 1567.53   283.3 1568.26   297.8 1568.17
   302.6 1569.01   307.4 1570.93   312.3 1573.68   321.9 1580.04   336.4 1590.60
   346.0 1598.45   360.5 1609.40   375.0 1619.89   379.8 1623.06   384.7 1625.90
#Mann= 3 , 0 , 0
       0     0.1       0   147.7   0.045       0   162.7     0.1       0
Bank Sta=   147.7,   162.7
Exp/Cntr=0.3,0.1

Type RM Length L Ch R = 1 ,1477.7,145.4,125.8,106.1
XS GIS Cut Line= 4
     1789075.025      280919.936     1789042.406      281019.376
     1788801.133      281055.335     1788709.596      281087.978
#Sta/Elev= 30
       0 1647.89    15.0 1647.91    49.8 1643.59    69.8 1635.52    84.7 1631.19
    89.7 1629.34   104.6 1623.12   129.6 1608.96   149.5 1598.30   159.4 1592.27
   174.4 1582.19   194.3 1566.65   199.2 1563.59   204.2 1561.01   209.2 1559.09
   214.2 1558.14   224.1 1556.96   235.1 1554.47   239.1 1553.39   244.0 1553.02
   250.1 1554.65   273.9 1561.62   278.9 1562.06   293.8 1562.48   313.7 1562.01
   348.6 1561.86   392.3 1562.33   411.8 1562.89   426.3 1562.71   445.8 1561.38
#Mann= 3 , 0 , 0
       0     0.1       0   235.1   0.045       0   250.1     0.1       0
Bank Sta=   235.1,   250.1
Exp/Cntr=0.3,0.1

Type RM Length L Ch R = 1 ,1351.9,205.6,229.9,254.2
XS GIS Cut Line= 4
     1789027.118      280875.146     1788869.445      280903.042
     1788807.516      280997.161     1788632.974      281075.583
#Sta/Elev= 30
       0 1620.13     9.7 1615.60    14.6 1614.56    24.3 1614.28    34.0 1613.02
    43.7 1610.65    53.4 1607.64    63.1 1603.88    77.6 1596.80    92.2 1590.58
   111.6 1579.67   116.4 1577.60   126.2 1574.39   135.9 1570.13   140.7 1568.59
   169.9 1566.99   184.6 1565.45   194.4 1563.50   203.2 1560.00   214.0 1554.48
   218.2 1553.27   218.9 1553.07   253.2 1560.38   282.6 1560.41   297.3 1561.18
   326.8 1561.73   366.0 1561.41   395.4 1563.22   410.2 1563.33   464.1 1566.63
#Mann= 3 , 0 , 0
       0     0.1       0   203.2   0.045       0   218.2     0.1       0
Bank Sta=   203.2,   218.2
Exp/Cntr=0.3,0.1

Type RM Length L Ch R = 1 ,1122.1,135.5,125.3,115.1
XS GIS Cut Line= 4
     1788975.959      280697.257     1788848.692      280759.087
     1788736.175      280753.287     1788583.143      280778.754
#Sta/Elev= 30
       0 1657.18    19.5 1641.66    24.4 1638.34    58.6 1618.27    73.2 1607.39
    92.7 1594.58    97.6 1590.77   117.1 1573.96   122.0 1570.23   126.8 1567.28
   131.7 1565.45   136.6 1564.57   161.1 1563.55   166.0 1561.60   170.9 1559.15
   195.4 1546.24   199.3 1545.77   200.3 1545.65   205.2 1547.30   214.3 1551.49
   219.9 1553.37   229.7 1554.51   263.8 1554.57   278.4 1555.18   307.5 1555.20
   336.6 1555.79   370.5 1555.70   380.2 1556.18   394.8 1556.23   409.3 1557.02
#Mann= 3 , 0 , 0
       0     0.1       0   199.3   0.045       0   214.3     0.1       0
Bank Sta=   199.3,   214.3
Exp/Cntr=0.3,0.1

Type RM Length L Ch R = 1 ,996.8,175,172.3,169.5
XS GIS Cut Line= 3
     1788955.400      280582.993     1788817.373      280614.108
     1788589.916      280710.036
#Sta/Elev= 30
       0 1677.88    14.6 1668.15    29.3 1657.30    34.2 1653.36    43.9 1644.87
    68.3 1621.02    73.2 1616.85    82.9 1611.49    97.6 1606.70   102.5 1604.32
   107.3 1601.38   117.1 1594.36   136.6 1578.72   156.3 1564.64   171.1 1552.72
   176.0 1549.22   181.0 1546.42   184.5 1545.41   185.9 1545.00   190.9 1545.58
   199.5 1547.88   210.6 1550.50   215.6 1551.11   245.2 1552.50   264.9 1552.64
   279.7 1552.32   309.4 1553.36   363.7 1552.26   373.5 1552.42   388.4 1553.29
#Mann= 3 , 0 , 0
       0     0.1       0   184.5   0.045       0   199.5     0.1       0
Bank Sta=   184.5,   199.5
Exp/Cntr=0.3,0.1

Type RM Length L Ch R = 1 ,824.5,213.4,212.2,211.1
XS GIS Cut Line= 3
     1788823.227      280370.992     1788731.536      280458.673
     1788507.643      280586.593
#Sta/Elev= 30
       0 1652.53    14.6 1642.84    29.3 1632.39    39.0 1624.44    48.8 1620.77
    68.3 1610.75    97.6 1596.48   102.5 1595.51   107.4 1593.72   112.2 1591.22
   122.0 1587.69   126.9 1585.39   136.8 1575.44   146.7 1569.31   171.5 1547.92
   176.5 1545.48   185.7 1542.35   191.3 1541.03   196.3 1542.62   200.7 1545.11
   206.2 1547.77   211.2 1548.89   226.0 1550.26   231.0 1550.42   245.9 1549.33
   255.8 1549.22   340.1 1552.19   345.1 1553.52   355.0 1557.44   384.7 1562.91
#Mann= 3 , 0 , 0
       0     0.1       0   185.7   0.045       0   200.7     0.1       0
Bank Sta=   185.7,   200.7
Exp/Cntr=0.3,0.1

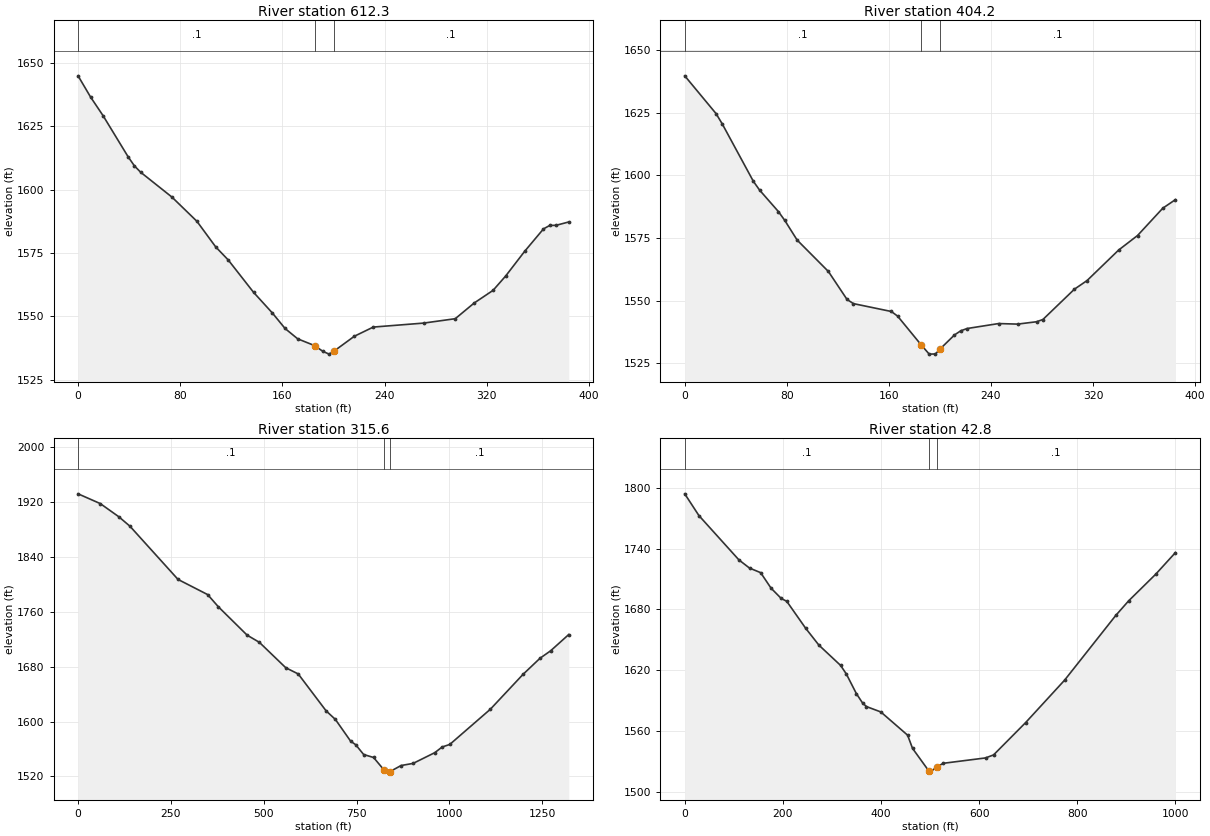
Type RM Length L Ch R = 1 ,612.3,200.9,208.1,215.2
XS GIS Cut Line= 3
     1788695.589      280194.875     1788613.219      280278.879
     1788388.826      280422.851
#Sta/Elev= 30
       0 1644.85     9.8 1636.48    19.6 1629.12    39.2 1612.92    44.1 1609.36
    49.0 1606.84    73.5 1597.04    93.1 1587.47   107.8 1577.38   117.6 1572.24
   137.4 1559.50   152.2 1551.31   162.1 1545.22   172.0 1541.14   185.2 1538.48
   191.7 1536.21   196.6 1535.11   200.2 1536.21   216.4 1542.17   231.2 1545.78
   270.7 1547.35   295.4 1549.08   310.2 1555.26   325.0 1560.26   334.9 1565.93
   349.7 1575.62   364.5 1584.50   369.4 1585.85   374.4 1585.91   384.3 1587.23
#Mann= 3 , 0 , 0
       0     0.1       0   185.2   0.045       0   200.2     0.1       0
Bank Sta=   185.2,   200.2
Exp/Cntr=0.3,0.1

Type RM Length L Ch R = 1 ,404.2,85.7,88.6,91.7
XS GIS Cut Line= 3
     1788625.570      280062.109     1788513.462      280122.284
     1788264.356      280187.015
#Sta/Elev= 30
       0 1639.74    24.5 1624.69    29.4 1620.55    53.8 1597.63    58.7 1594.11
    73.4 1585.57    78.3 1582.11    88.1 1574.19   112.6 1561.65   127.2 1550.49
   132.2 1548.83   161.9 1545.69   166.8 1543.86   185.4 1532.31   191.6 1528.67
   196.5 1528.74   200.4 1530.85   211.4 1536.32   216.3 1537.97   221.3 1538.89
   246.0 1540.87   260.9 1540.65   275.7 1541.59   280.7 1542.48   305.4 1554.58
   315.3 1558.02   340.1 1570.22   354.9 1576.01   374.7 1586.92   384.6 1590.33
#Mann= 3 , 0 , 0
       0     0.1       0   185.4   0.045       0   200.4     0.1       0
Bank Sta=   185.4,   200.4
Exp/Cntr=0.3,0.1

Type RM Length L Ch R = 1 ,315.6,271.3,272.8,274.1
XS GIS Cut Line= 6
     1789172.264      280212.405     1788899.685      279994.440
     1788732.338      280015.752     1788684.620      280021.705
     1788679.241      280022.474     1787935.060      280116.756
#Sta/Elev= 30
       0 1931.55    59.8 1917.33   109.7 1898.17   139.6 1884.44   269.2 1806.90
   349.0 1784.82   377.8 1767.06   455.2 1725.81   488.2 1715.33   559.3 1678.34
   592.9 1669.27   668.0 1615.53   693.0 1603.03   734.1 1571.34   747.5 1566.32
   769.1 1551.97   795.8 1547.64   824.8 1528.90   833.4 1526.33   839.8 1527.05
   869.8 1535.94   902.3 1539.04   960.6 1554.67   980.6 1562.94  1001.0 1566.64
  1110.4 1617.95  1198.2 1668.64  1244.2 1692.22  1272.4 1702.90  1321.5 1726.72
#Mann= 3 , 0 , 0
       0     0.1       0   824.8   0.045       0   839.8     0.1       0
Bank Sta=   824.8,   839.8
Exp/Cntr=0.3,0.1

Type RM Length L Ch R = 1 ,42.8,43.2,42.8,42.3
XS GIS Cut Line= 6
     1788856.573      279763.435     1788232.502      279800.785
     1788198.804      279802.897     1788158.766      279805.201
     1788145.996      279806.064     1787858.348      279823.250
#Sta/Elev= 30
       0 1794.12    28.9 1772.63   110.5 1728.82   132.0 1720.79   154.7 1716.25
   175.9 1700.94   196.7 1690.74   207.9 1687.96   246.4 1661.35   273.4 1644.68
   317.7 1624.61   329.4 1616.12   349.9 1596.68   362.7 1587.33   370.4 1583.96
   399.6 1578.68   454.2 1555.73   464.2 1542.72   498.2 1519.89   500.1 1519.22
   513.2 1524.20   526.9 1527.94   613.0 1533.24   629.4 1536.22   694.9 1568.22
   774.1 1610.02   878.4 1673.95   904.8 1688.46   959.6 1714.57  1000.1 1736.09
#Mann= 3 , 0 , 0
       0     0.1       0   498.2   0.045       0   513.2     0.1       0
Bank Sta=   498.2,   513.2
Exp/Cntr=0.3,0.1